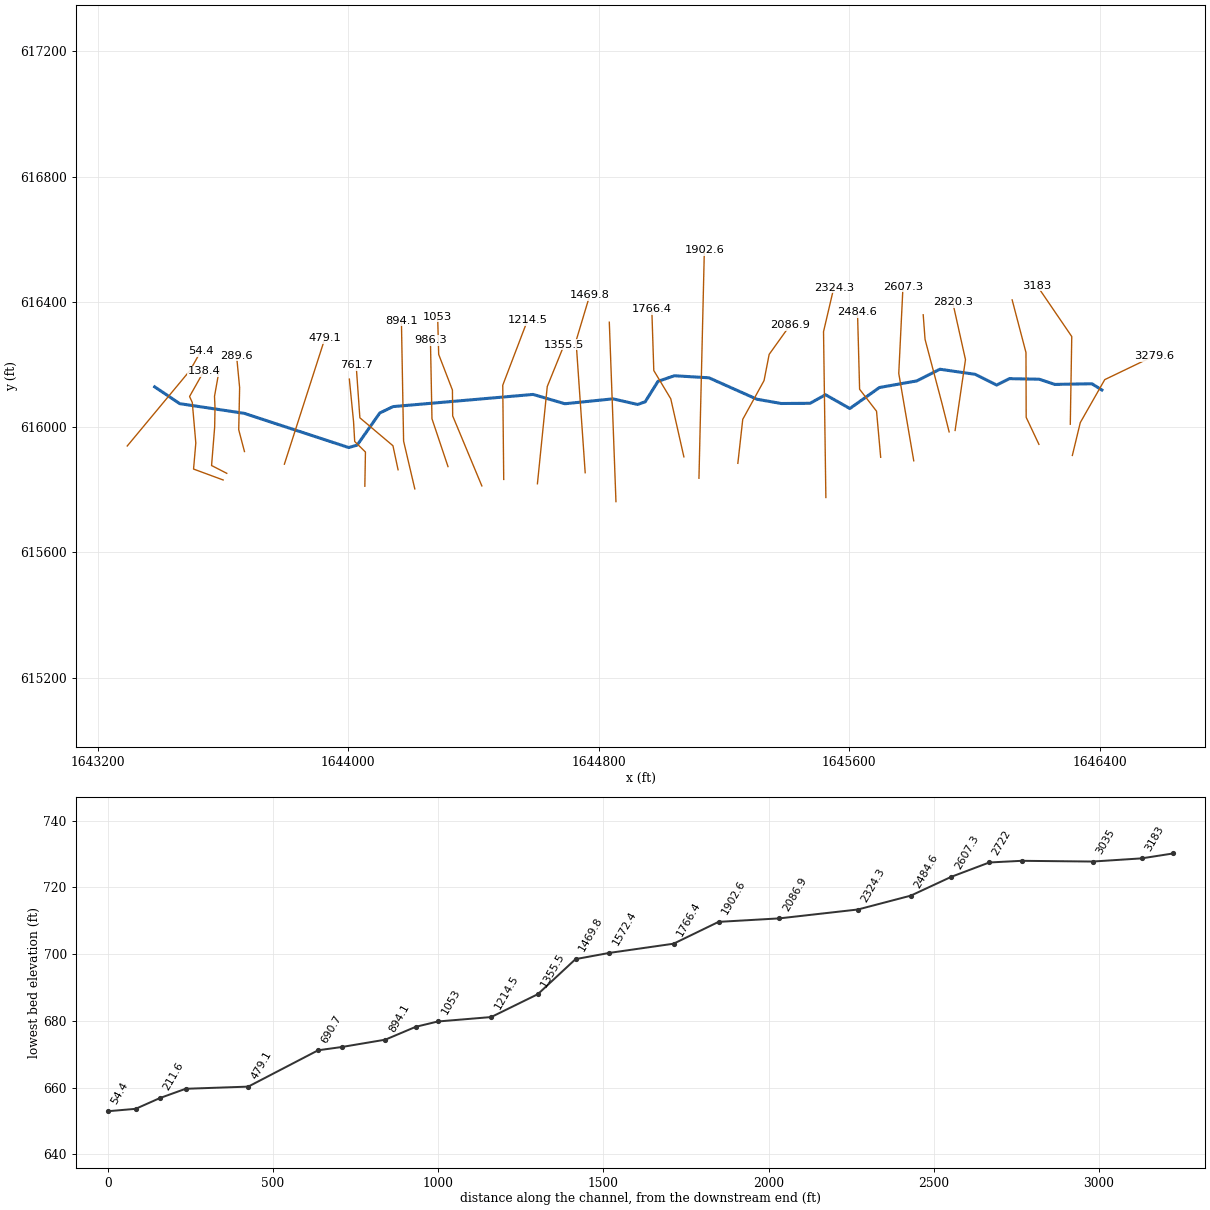
--- GIRTYRUN.prj (project) ---

Proj Title=GIRTYRUN
Current Plan=p01
Default Exp/Contr=0,0
English Units
Geom File=g01
Flow File=f01
Plan File=p01
BEGIN DESCRIPTION:
END DESCRIPTION:
DSS Export Rating Curves= 0
DSS Export Rating Curve Sorted= 0
DSS Export Volume Flow Curves= 0
DXF Filename=..\..\..\..\..\Engineering\Hydraulics\GIRTYRUN\GIRTYRUN.
DXF OffsetX= 0
DXF OffsetY= 0
DXF ScaleX= 0
DXF ScaleY= 0

--- GIRTYRUN.p01 (plan) ---

Plan Title=Floodplain
Program Version=4.00
Geom File=g01
Flow File=f01
K Sum by GR=0
Std Step Tol=0.01
Critical Tol=0.01
Num of Std Step Trials=20
Max Error Tol=0.3
Flow Tol Ratio=0.001
Split Flow NTrial=30
Split Flow Tol=0.02
Split Flow Ratio=0.02
Log Output Level=0
Friction Slope Method=1
Unsteady Friction Slope Method=2
Unsteady Bridges Friction Slope Method=1
Global Log Level=0
CheckData=False
Run HTab=0
Run UNet=0
Run PostProcess=0
UNET Theta=0
UNET Theta Warmup=0
UNET ZTol=0
UNET ZSATol=0
UNET MxIter=0
UNET MaxInSteps=0
UNET DtIC=0
UNET DtMin=0
UNET MaxCRTS=0
UNET WFStab=0
UNET SFStab=0
UNET WFX=0
UNET SFX=0
UNET DSS MLevel=0
UNET DZMax Abort=0
UNET Convert EG Bridges=0
UNET Use Existing IB Tables=0
UNET Froude Limit=0
UNET Froude Power=0
Write IC File=0
Echo Input=False
Echo Output=False
Write Detailed=0

--- GIRTYRUN.f01 (steady flow) ---

Flow Title=NFF Regression Equation
Program Version=4.10
Number of Profiles= 1
Profile Names=P100yr
River Rch & RM=GIRTYRUN,Main            ,3279.6
1050.133
River Rch & RM=GIRTYRUN,Main            ,894.1
1087.634
River Rch & RM=GIRTYRUN,Main            ,289.6
1101.184
Boundary for River Rch & Prof#=GIRTYRUN,Main            , 1
Up Type= 0
Dn Type= 3
Dn Slope=0.03
DSS Import GetInterval= 0
DSS Import GetPeak= 0
DSS Import FillOption= 0

--- GIRTYRUN.g01 (geometry) ---

Geom Title=2003 WVU SAMB 3 Meter DEM
Program Version=4.10

River Reach=GIRTYRUN        ,Main
Reach XY= 30
     1646406.556      616118.721     1646374.655      616138.687
     1646256.145      616136.569     1646206.709      616153.149
     1646111.353      616154.971     1646070.662      616134.542
     1646001.612      616168.914     1645889.214      616185.045
      1645815.52      616147.767     1645696.249      616126.673
     1645601.811      616059.598      1645524.11      616103.621
     1645474.895      616076.326     1645382.881      616075.631
      1645305.12      616089.242     1645151.978      616157.662
      1645041.81      616164.259     1644989.359      616146.457
     1644948.416      616081.138     1644924.374      616072.506
     1644845.208      616090.475     1644691.822       616074.85
     1644590.343      616104.576     1644143.436      616065.751
     1644100.937      616045.423     1644028.711       615942.77
     1644001.801      615934.958       1643667.6      616044.333
     1643462.135       616075.11     1643382.187      616128.756

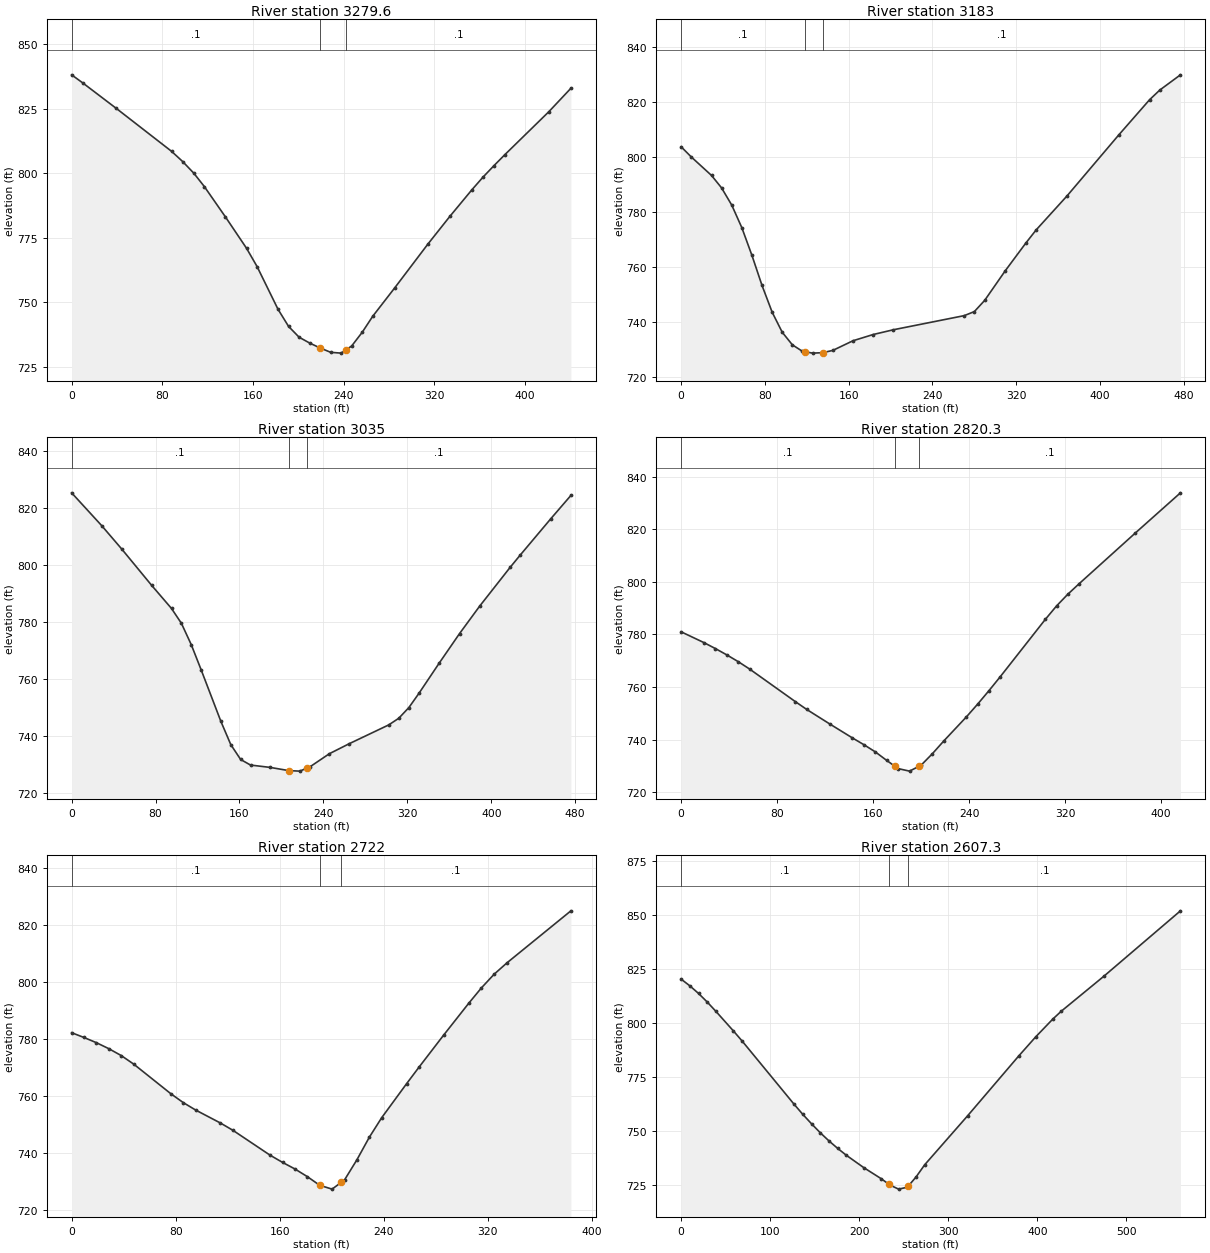
Type RM Length L Ch R = 1 ,3279.6  ,84.8,96.6,107.7
XS GIS Cut Line= 4
     1646312.273      615909.804     1646337.563      616014.623
     1646415.684      616151.829     1646573.211      616227.512
#Sta/Elev= 30
       0  838.11     9.8  834.98    39.2  825.16    88.2  808.44      98  804.47
   107.8  799.97   117.1  794.78   135.7  783.02   154.3  770.87   163.6  763.78
   182.1   747.2   191.4  740.56   200.7  736.37     210  734.11   219.3  732.18
   228.6  730.51   237.8   730.2   242.1  731.49   247.1  732.98   256.4   738.3
   265.7  744.52   285.1  755.53   314.3  772.47   333.7  783.22   353.1  793.51
   362.8  798.37   372.5  802.84   382.2  807.14   421.1  823.84   440.5   832.9
#Mann= 3 , 0 , 0
       0      .1       0   219.3    .045       0   242.1      .1       0
Bank Sta=219.3,242.1
XS Rating Curve= 0 ,0
Exp/Cntr=0.3,0.1

Type RM Length L Ch R = 1 ,3183    ,146.8,148,147.7
XS GIS Cut Line= 3
     1646305.695      616009.524     1646310.376      616289.438
     1646199.494      616452.072
#Sta/Elev= 30
       0  803.73     9.6  800.06      29  793.31    38.6  788.78    48.3  782.53
    57.9  774.35    67.6  764.23    77.2  753.33    86.9  743.58    96.5   736.3
   106.2  731.72   115.8  729.37   118.4  729.19   125.5  728.71   135.2  728.87
   144.8   729.7   164.1  733.21   183.4  735.48   202.7  737.21   270.3  742.34
     280  743.82   289.8  747.87   309.5  758.66   329.2  768.76     339  773.51
   368.5  785.88   417.7  807.96   447.3  820.84   457.1  824.37   476.8   829.9
#Mann= 3 , 0 , 0
       0      .1       0   118.4    .045       0   135.2      .1       0
Bank Sta=118.4,135.2
XS Rating Curve= 0 ,0
Exp/Cntr=0.3,0.1

Type RM Length L Ch R = 1 ,3035    ,218.3,214.6,207.7
XS GIS Cut Line= 4
     1646205.503      615945.242     1646164.826      616031.352
     1646164.172      616238.301     1646120.086      616406.353
#Sta/Elev= 30
       0   825.3    28.6  813.82    47.6  805.67    76.2   792.9    95.2  784.77
   104.6  779.59     114  772.11   123.4  763.32   142.3  745.17   151.7  737.06
   161.1  731.84   170.5  729.89   189.3  729.06     207727.9402   217.5  727.76
     224  728.76   226.9   729.2   245.7  733.87   264.6  737.37   302.2  743.95
   311.8  746.28   321.5  750.06   331.1  755.05   350.4  765.64   369.8  775.99
     389  785.62     418  799.19   427.7  803.53   456.6  816.16   475.9  824.39
#Mann= 3 , 0 , 0
       0      .1       0     207    .045       0     224      .1       0
Bank Sta=207,224
XS Rating Curve= 0 ,0
Exp/Cntr=0.3,0.1

Type RM Length L Ch R = 1 ,2820.3  ,89.2,98.3,107.5
XS GIS Cut Line= 3
     1645937.899       615989.55     1645971.011      616215.652
     1645930.208      616398.936
#Sta/Elev= 30
       0  780.95      19  776.85    28.6  774.57    38.1  772.17    47.6   769.6
    57.1  766.79    95.2  754.41   104.7  751.43   123.8  745.94   142.8   740.6
   152.3  738.05   161.9  735.29   171.4  732.04     178729.8863   180.9  728.94
   190.4  727.98     198729.7433     200  730.21   209.5  734.62     219  739.47
   237.9  748.64   247.3  753.51   256.7  758.61   266.1  763.91   303.6  785.67
     313   790.8   322.4  795.25   331.8  799.24   378.7  818.54   416.3  833.81
#Mann= 3 , 0 , 0
       0      .1       0     178    .045       0     198      .1       0
Bank Sta=178,198
XS Rating Curve= 0 ,0
Exp/Cntr=0.3,0.1

Type RM Length L Ch R = 1 ,2722    ,116.5,114.7,112.4
XS GIS Cut Line= 4
     1645918.838      615984.943     1645895.585      616077.425
     1645841.958      616280.418     1645836.025      616358.902
#Sta/Elev= 30
       0  782.28     9.5   780.6    19.1  778.77    28.6  776.68    38.1  774.28
    47.7  771.29    76.3   760.9    85.8  757.81    95.4  755.18   114.4  750.65
     124   748.1   152.6  739.38   162.2  736.85   171.7  734.55   181.2  731.88
   190.8  728.83   200.3  727.48   207.5   729.9   209.9  730.71   219.4  737.75
     229  745.69   238.5  752.52   257.6   764.4   267.1  770.16   286.2  781.48
   305.3  792.52   315.2  797.99     325  802.78   334.8  806.74     384  824.97
#Mann= 3 , 0 , 0
       0      .1       0   190.8    .045       0   207.5      .1       0
Bank Sta=190.8,207.5
XS Rating Curve= 0 ,0
Exp/Cntr=0.3,0.1

Type RM Length L Ch R = 1 ,2607.3  ,111.4,122.7,133.6
XS GIS Cut Line= 3
     1645805.827       615892.66        1645758.      616171.791
     1645771.476      616448.888
#Sta/Elev= 30
       0  820.39     9.8  817.27    19.5  813.78    29.3  809.78    39.1  805.44
    58.6  796.45    68.4  791.77     127  762.38   136.7  757.74   146.5  753.38
   156.2  749.28     166  745.49   175.8  742.03   185.5  738.85   205.1  733.12
   224.6  728.02     233725.5086   234.4  725.09   244.1  723.19   253.9  724.07
     255   724.6   263.7   728.8   273.4  734.45   321.5  757.08   378.9  784.78
     398  793.64   417.1  801.84   426.7  805.52   474.5   821.7   560.6  852.02
#Mann= 3 , 0 , 0
       0      .1       0     233    .045       0     255      .1       0
Bank Sta=233,255
XS Rating Curve= 0 ,0
Exp/Cntr=0.3,0.1

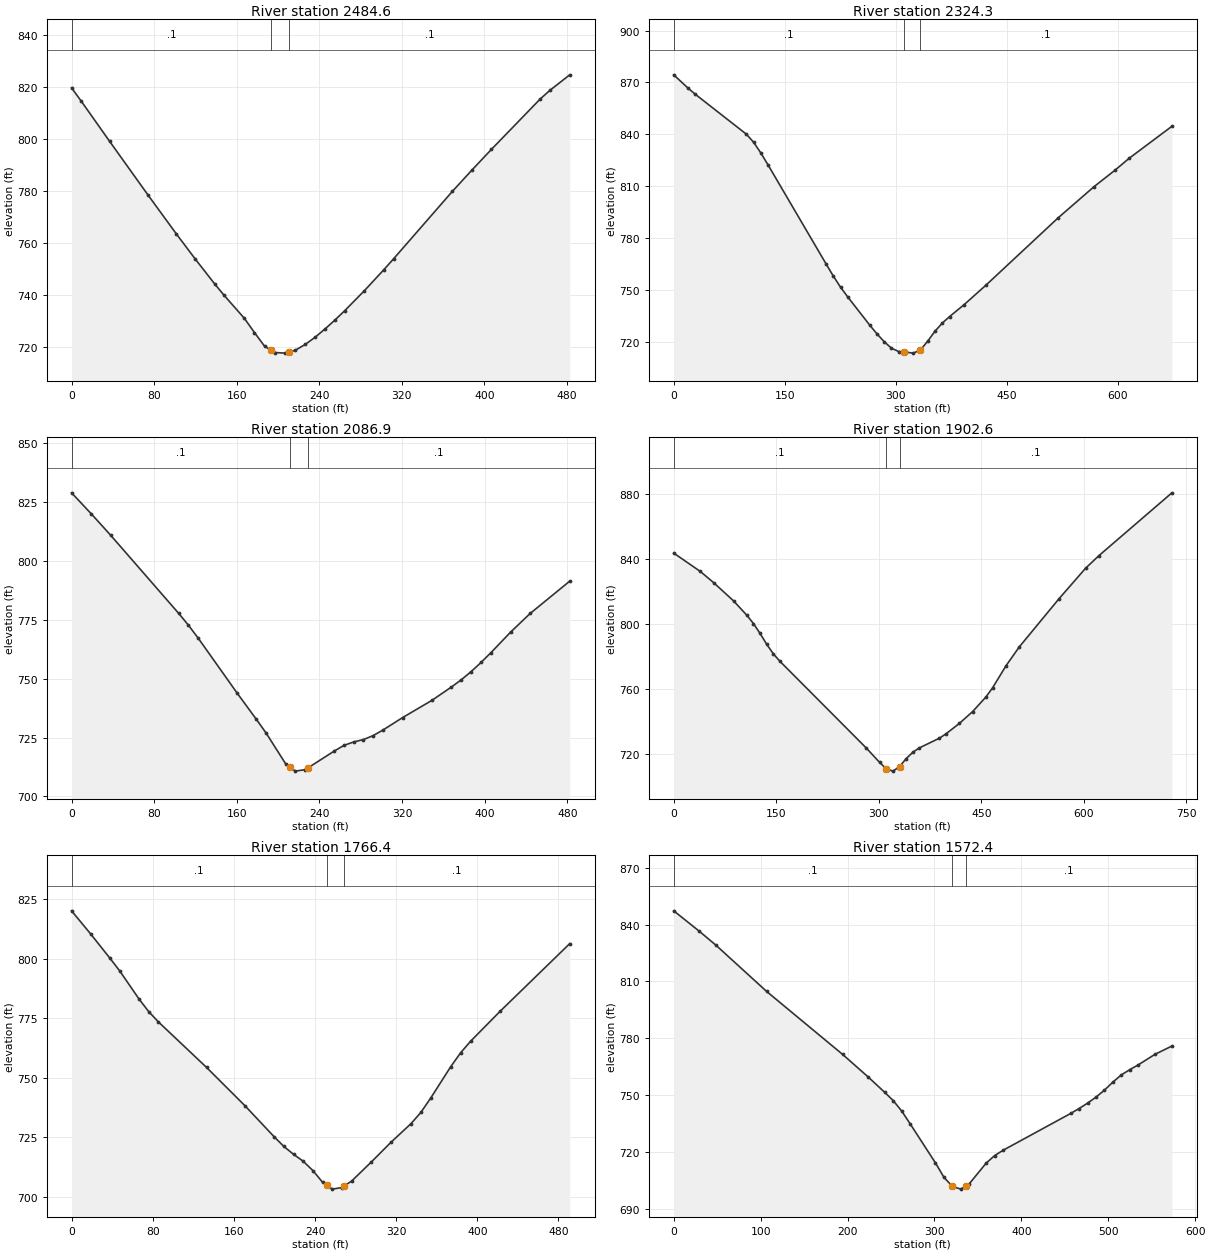
Type RM Length L Ch R = 1 ,2484.6  ,173.7,160.3,143.8
XS GIS Cut Line= 4
     1645700.264      615903.884     1645687.013      616050.982
     1645632.968      616121.107     1645626.262      616367.469
#Sta/Elev= 30
       0  819.53     9.2  814.51    36.9  798.95    73.8  778.47   101.5  763.39
     120  753.64   138.5  744.24   147.7  739.81   167.4  730.93   177.2  725.45
     187  720.21   193.3  718.66   196.9  717.78   206.7  717.54     211718.0028
   216.6  718.61   226.4  720.88   236.2  723.71   245.7  726.88   255.2  730.26
   264.7  733.87   283.6  741.49   302.6  749.63   312.1  753.84   368.9   779.7
   387.9  787.91   406.8  795.87   454.2   815.3   463.7  818.64   482.7  824.54
#Mann= 3 , 0 , 0
       0      .1       0   193.3    .045       0     211      .1       0
Bank Sta=193.3,211
XS Rating Curve= 0 ,0
Exp/Cntr=0.3,0.1

Type RM Length L Ch R = 1 ,2324.3  ,248.8,237.5,224.7
XS GIS Cut Line= 3
      1645525.24      615775.431     1645517.767      616304.893
     1645550.438      616444.682
#Sta/Elev= 30
       0   874.4    19.6  866.59    29.4  863.07    98.1  840.07   107.9  835.43
   117.7  829.18   127.5  822.22   205.9  764.96   215.7  757.91   225.5  751.46
   235.3  745.79   264.8  729.59   274.6  724.52   284.4  719.97   294.2  716.24
     304   714.3     311714.0928   323.6  713.38   333.4  715.21   343.2  720.34
     353  726.05   362.8  730.74   372.6  734.49   392.2  741.37   421.6   752.6
   519.7  791.77   567.8  809.65   596.5  819.32   615.6   826.2   673.1  844.62
#Mann= 3 , 0 , 0
       0      .1       0     311    .045       0   333.4      .1       0
Bank Sta=311,333.4
XS Rating Curve= 0 ,0
Exp/Cntr=0.3,0.1

Type RM Length L Ch R = 1 ,2086.9  ,173.1,184.2,194.8
XS GIS Cut Line= 5
     1645244.185      615884.596     1645259.865      616025.104
     1645327.835      616148.761     1645344.185      616232.513
     1645410.852      616325.568
#Sta/Elev= 30
       0  828.93    18.8  820.14    37.7  810.99   103.7  777.73   113.1  772.72
   122.5  767.27   160.2  743.92     179  732.67   188.4  726.86   207.2  713.87
   211.2  712.53   216.6  710.72     226  711.34     229712.1296   254.3  719.24
   263.7  721.66   273.1  723.11   282.5  724.12     292  725.81   301.4  728.16
   320.4  733.44   348.9  740.79   367.8  746.46   377.4  749.56   386.9  753.02
   396.4  756.87     406  761.04   425.1  769.78   444.1  777.73   482.3  791.42
#Mann= 3 , 0 , 0
       0      .1       0   211.2    .045       0     229      .1       0
Bank Sta=211.2,229
XS Rating Curve= 0 ,0
Exp/Cntr=0.3,0.1

Type RM Length L Ch R = 1 ,1902.6  ,123.2,136.2,148.9
XS GIS Cut Line= 2
     1645119.999      615836.925     1645137.238      616565.519
#Sta/Elev= 30
       0  843.61    38.9  832.32    58.3  825.49    87.5  814.26   106.9  805.46
   116.6  800.34   126.3  794.25     136   787.6   145.8  781.67   155.5  777.08
   281.8  723.82   301.2  715.03     311   711.1   320.7  709.67   330.3  712.43
   340.1  717.36   349.8  721.28   359.5  723.98   388.7  729.91   398.4  732.61
   417.8  738.95   437.3  746.27   456.7   755.2   466.4  760.81   485.9  774.26
   505.3  785.86   563.6  815.55   602.5   834.3   621.9     842   728.8  880.63
#Mann= 3 , 0 , 0
       0      .1       0     311    .045       0   330.3      .1       0
Bank Sta=311,330.3
XS Rating Curve= 0 ,0
Exp/Cntr=0.3,0.1

Type RM Length L Ch R = 1 ,1766.4  ,205,194,181.2
XS GIS Cut Line= 4
      1645071.87      615905.223        1645030.       616090.69
     1644975.817      616180.925     1644969.439      616376.577
#Sta/Elev= 30
       0  820.22      19   810.4      38  800.18    47.5  794.92    66.6  783.05
      76  777.83    85.6  773.48   133.1  754.32   171.1  738.13   199.7  725.16
   209.3  721.06   218.8  717.78   228.4  714.84     238  710.88   247.5  705.97
   251.5  704.78   257.1  703.12   266.5  703.79     269704.5013   276.2  706.55
   295.4   714.5     315  722.89   334.5  730.62   344.3  735.38   354.1  741.48
   373.7  754.59   383.5  760.48   393.3  765.32   422.6  778.01   491.1  806.42
#Mann= 3 , 0 , 0
       0      .1       0   251.5    .045       0     269      .1       0
Bank Sta=251.5,269
XS Rating Curve= 0 ,0
Exp/Cntr=0.3,0.1

Type RM Length L Ch R = 1 ,1572.4  ,101.7,102.6,103.2
XS GIS Cut Line= 2
      1644854.99      615762.266     1644833.748      616335.216
#Sta/Elev= 30
       0  847.22    29.2  836.53    48.6  829.07   106.9  804.69   194.4  771.44
   223.5  759.66   242.9   751.4   252.7  747.03   262.4  741.54   272.1  734.82
   301.2   714.2     311  706.58   320.8  701.77   330.4  700.37   335.8  701.94
   340.1  703.19   359.6  714.12   369.3  718.06     379  720.87   456.7  740.28
   466.4  742.86   476.2  745.73   485.9   748.9   495.6  752.57   505.3   756.8
     515  760.62   524.8  763.41   534.5  765.92   553.9  771.52   573.3  775.87
#Mann= 3 , 0 , 0
       0      .1       0   320.8    .045       0   335.8      .1       0
Bank Sta=320.8,335.8
XS Rating Curve= 0 ,0
Exp/Cntr=0.3,0.1

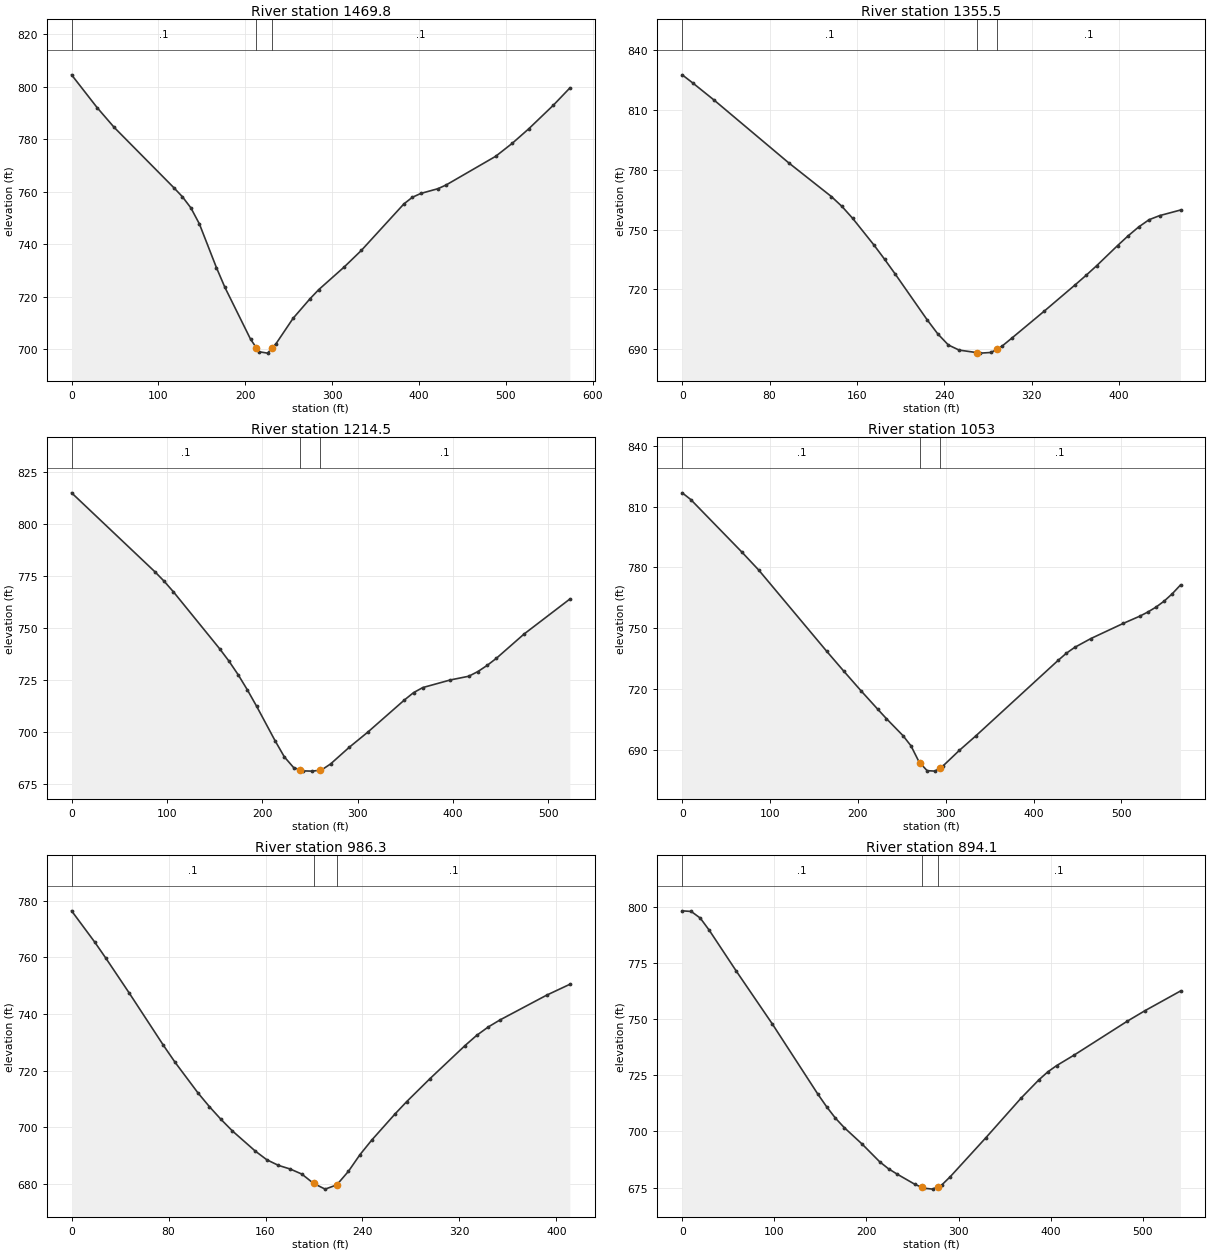
Type RM Length L Ch R = 1 ,1469.8  ,117.4,114.3,110.3
XS GIS Cut Line= 3
     1644756.748      615854.612     1644727.516      616275.322
     1644771.206      616420.834
#Sta/Elev= 30
       0  804.46    29.4  791.98      49  784.47   117.7  761.49   127.5  758.07
   137.3  753.82   147.1  747.72   166.7   731.1   176.5  723.54     206  703.82
   212.5700.6391   215.8  699.02   225.6   698.5   230.4  700.27   235.4  702.12
     255  711.76   274.6  719.25   284.4  722.64   313.8  731.29   333.5  737.58
   382.5   755.3   392.3  757.84   402.1  759.31   421.7   761.1   431.2  762.53
   488.2  773.44   507.2  778.36   526.2  783.89   554.7  792.93   573.6  799.46
#Mann= 3 , 0 , 0
       0      .1       0   212.5    .045       0   230.4      .1       0
Bank Sta=212.5,230.4
XS Rating Curve= 0 ,0
Exp/Cntr=0.3,0.1

Type RM Length L Ch R = 1 ,1355.5  ,138.8,141,143.1
XS GIS Cut Line= 3
     1644604.223      615819.273     1644635.628      616129.811
     1644689.793      616263.584
#Sta/Elev= 30
       0  827.71     9.8  823.57    29.3  814.98    97.5  783.54   136.6  766.61
   146.3  761.65   156.1  755.66   175.6  742.28   185.3  735.16   195.1  727.69
   224.3  704.75   234.1  697.64   243.8  692.06   253.6  689.51     270688.2292
   273.1  687.98   282.9  688.31   288.2  689.96   292.6  691.33   302.4  695.74
   331.4  708.97   360.2   722.4   369.8  726.98   379.5  731.82   398.7  741.95
   408.3   746.8     418  751.29   427.6  754.96   437.2  757.01   456.4  759.83
#Mann= 3 , 0 , 0
       0      .1       0     270    .045       0   288.2      .1       0
Bank Sta=270,288.2
XS Rating Curve= 0 ,0
Exp/Cntr=0.3,0.1

Type RM Length L Ch R = 1 ,1214.5  ,161.4,161.5,161.5
XS GIS Cut Line= 3
     1644496.614      615833.119     1644493.541      616133.963
     1644572.562      616341.231
#Sta/Elev= 30
       0  815.08    87.4  777.09      97  772.58   106.8  767.45   155.3  740.04
     165  734.14   174.7  727.56   184.4  720.24   194.1  712.36   213.5  695.74
   223.2  687.98   232.9  682.85     240681.6862   242.6  681.26   252.3  681.13
   260.9  681.57     262  681.63   271.7  684.59   291.2  692.58   310.5  699.81
   349.1  715.36   358.7   718.9   368.4  721.35   397.3  725.01   416.6   726.8
   426.2  729.05   435.9  732.01   445.5  735.39   474.5  747.06   522.7  763.96
#Mann= 3 , 0 , 0
       0      .1       0     240    .045       0   260.9      .1       0
Bank Sta=240,260.9
XS Rating Curve= 0 ,0
Exp/Cntr=0.3,0.1

Type RM Length L Ch R = 1 ,1053    ,66.5,66.7,66.9
XS GIS Cut Line= 5
     1644426.729      615812.499     1644333.656      616036.015
      1644332.85      616118.472     1644288.925       616232.42
      1644285.67      616352.863
#Sta/Elev= 30
       0  816.74     9.7  813.45    67.8  787.64    87.2  778.69   164.6  738.71
     184  728.96   203.4   719.4   222.8  710.15   232.4  705.65   251.3  697.27
   260.4  692.26   269.6  684.33   271.1  683.63   278.8  680.03   287.9   679.8
   293.1   681.3   297.1  682.45   315.4  689.99     334  697.06   427.9   734.3
   437.3  737.82   446.7  740.68   465.2  745.04   502.3  752.54   520.8  756.04
   530.1   758.1   539.4  760.53   548.6  763.46   557.9  767.11   567.2   771.4
#Mann= 3 , 0 , 0
       0      .1       0   271.1    .045       0   293.1      .1       0
Bank Sta=271.1,293.1
XS Rating Curve= 0 ,0
Exp/Cntr=0.3,0.1

Type RM Length L Ch R = 1 ,986.3   ,92.2,92.2,92.1
XS GIS Cut Line= 3
     1644318.664      615874.179      1644267.52      616026.975
     1644262.652       616276.93
#Sta/Elev= 30
       0  776.38      19  765.41    28.4   759.6    47.4  747.49    75.8  728.92
    85.3     723   104.3  712.14   113.7  707.31   123.2  702.85   132.7  698.73
   151.6  691.62   161.1  688.56   170.7  686.58   180.4   685.3     190  683.51
   199.6  680.24   209.2  678.21   218.8  679.71   228.4  684.49     238  690.41
   247.7  695.54   266.9  704.75   276.5  709.09   295.7  717.19   324.6  728.85
   334.2  732.44   343.8  735.42   353.4  737.88   391.9  746.62   411.1  750.47
#Mann= 3 , 0 , 0
       0      .1       0   199.6    .045       0   218.8      .1       0
Bank Sta=199.6,218.8
XS Rating Curve= 0 ,0
Exp/Cntr=0.3,0.1

Type RM Length L Ch R = 1 ,894.1   ,112.9,132.4,151.5
XS GIS Cut Line= 3
       1644212.7       615802.98     1644176.925      615955.534
     1644169.955      616339.544
#Sta/Elev= 30
       0  798.09     9.8  797.81    19.6  794.86    29.4  789.43    58.8  771.23
    97.9  747.73   146.9  716.79   156.7     711   166.3  705.91   175.9  701.69
   195.1  694.45   214.3  686.52   223.9   683.4   233.5  680.97   252.7  676.45
     260675.1725   262.3  674.77   271.9  674.35   277.6   675.4   281.5  676.12
   291.1  679.96   329.5  697.18   367.9  714.87   387.1  722.95   396.7  726.46
   406.3  729.26   425.5  733.99   483.2  749.06   502.4  753.73   540.8  762.44
#Mann= 3 , 0 , 0
       0      .1       0     260    .045       0   277.6      .1       0
Bank Sta=260,277.6
XS Rating Curve= 0 ,0
Exp/Cntr=0.3,0.1

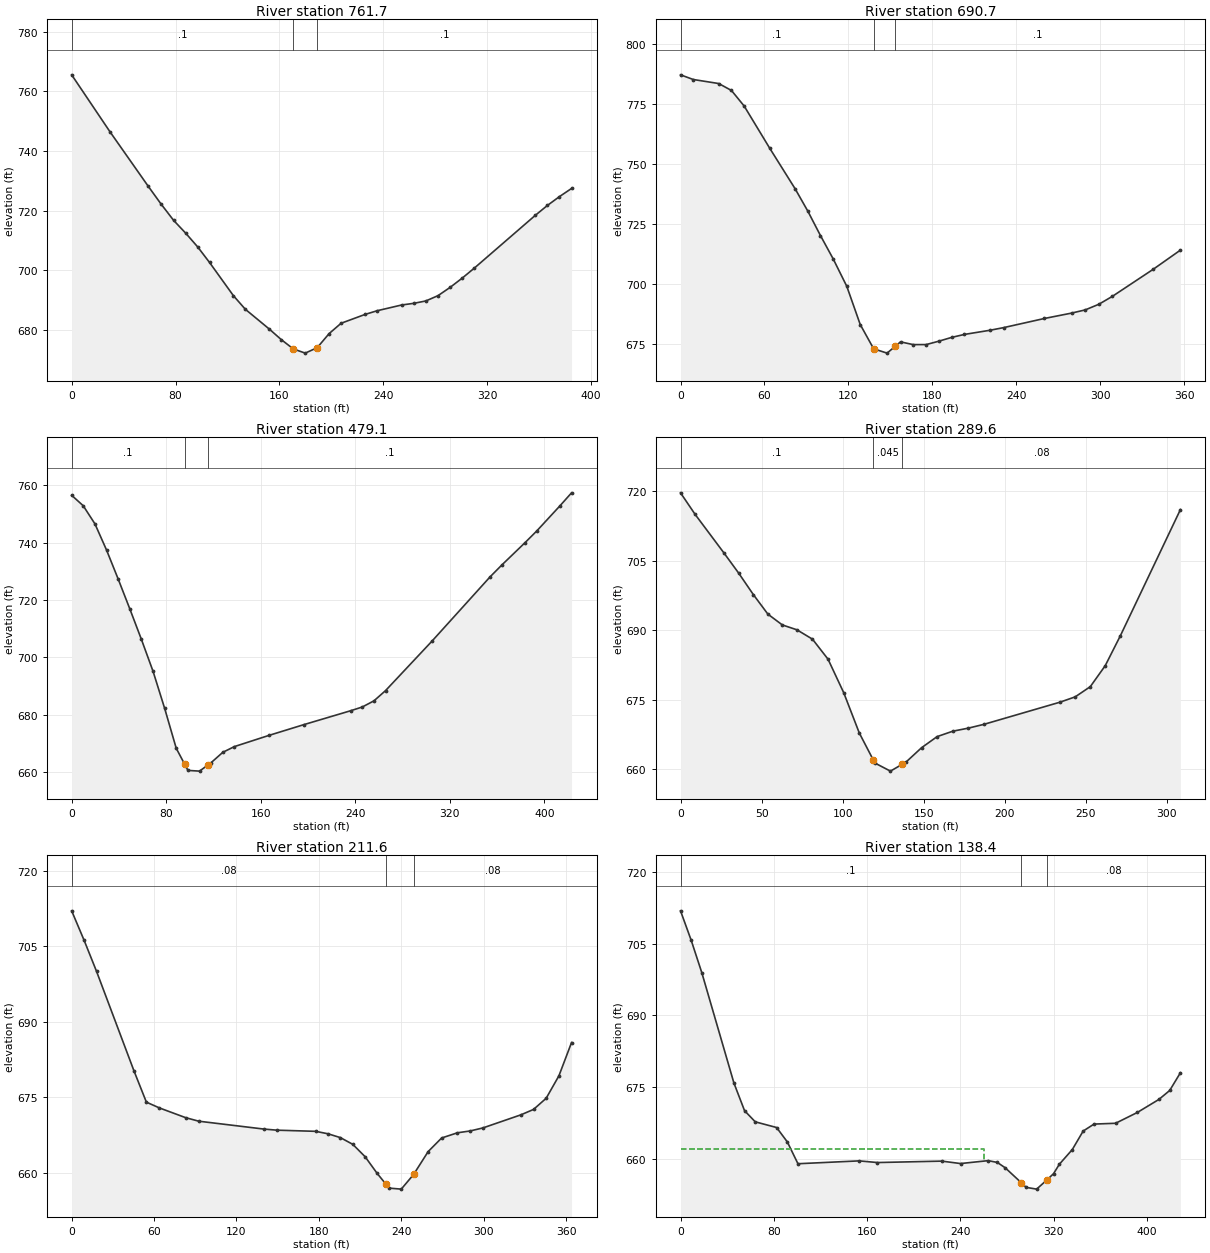
Type RM Length L Ch R = 1 ,761.7   ,72.5,71,56
XS GIS Cut Line= 4
     1644159.289      615863.971     1644142.911       615940.78
     1644037.322      616029.911     1644025.435      616197.825
#Sta/Elev= 30
       0  765.53    29.4  746.49    58.9  728.18    68.7  722.26    78.5   716.7
    87.8  712.41      97  707.81   106.2  702.56   124.6   691.4   133.8  686.84
   152.2  680.22   161.4  676.69   170.7  673.55   179.9  672.14   189.1  673.97
   198.3   678.7   207.5  682.16   226.1  685.15   235.4  686.38   254.1  688.29
   263.5  688.85   272.8  689.65   282.2  691.44   291.5  694.21   300.9  697.35
   310.2   700.7     357  718.35   366.4   721.7   375.7  724.67     385   727.4
#Mann= 3 , 0 , 0
       0      .1       0   170.7    .045       0   189.1      .1       0
Bank Sta=170.7,189.1
XS Rating Curve= 0 ,0
Exp/Cntr=0.3,0.1

Type RM Length L Ch R = 1 ,690.7   ,237,211.6,199.2
XS GIS Cut Line= 5
     1644053.169      615811.519     1644055.085      615920.643
     1644020.791      615954.314     1644017.102      616018.114
      1644003.69      616153.533
#Sta/Elev= 30
       0  787.15     9.1   785.2    27.3  783.52    36.4  780.63    45.5  774.12
    63.7  756.59    81.9  739.65      91   730.3     100  720.15   109.1  710.42
   118.8  699.02   128.4   683.1     138  672.97   147.6  671.17   153.5674.0524
   157.2  675.86   166.3  674.72   175.5  674.73   184.6  676.15   193.7  677.72
   202.8  678.96   221.1   680.7   230.8  681.79     260  685.61   279.4  687.85
   289.2  689.19   298.9  691.53   308.6  694.84   337.8  706.13   357.2   714.1
#Mann= 3 , 0 , 0
       0      .1       0     138    .045       0   153.5      .1       0
Bank Sta=138,153.5
XS Rating Curve= 0 ,0
Exp/Cntr=0.3,0.1

Type RM Length L Ch R = 1 ,479.1   ,182.8,189.6,195.9
XS GIS Cut Line= 2
     1643796.257      615881.924     1643925.952      616284.549
#Sta/Elev= 30
       0  756.58     9.8  752.92    19.7   746.6    29.5  737.48    39.4   727.3
    49.2  716.93      59  706.29    68.9  695.09    78.7  682.16    88.5  668.23
    95.5  662.78    98.4  660.52   108.2  660.27     115 662.316     118  663.22
   127.9  666.84   137.7  668.84   167.2  672.78   196.7  676.53   236.1  681.36
   245.9  682.66   255.8  684.81   265.6  688.38     305   705.7   354.1  728.12
     364  732.24   383.6  740.03   393.5   744.1   413.2  752.91     423  757.44
#Mann= 3 , 0 , 0
       0      .1       0    95.5    .045       0     115      .1       0
Bank Sta=95.5,115
XS Rating Curve= 0 ,0
Exp/Cntr=0.3,0.1

Type RM Length L Ch R = 1 ,289.6   ,77.4,78,78.7
XS GIS Cut Line= 4
     1643668.786      615922.264     1643650.499      615991.718
     1643653.355      616126.272     1643643.613       616227.82
#Sta/Elev= 28
       0  719.68       9  715.03    26.9  706.65    35.9  702.34    44.9  697.73
    53.9   693.5    62.8  691.17    71.8  690.12    81.4   688.1      91  683.78
   100.7  676.53   110.3  667.84   118.8  662.11   119.9  661.37   129.5  659.62
   136.8661.1013   139.1  661.57   148.7  664.67   158.3  667.07     168  668.24
   177.6   668.9   187.2  669.72   234.2  674.51   243.5  675.65   252.8  677.85
     262  682.37   271.3   688.8   308.4  716.07
#Mann= 3 , 0 , 0
       0      .1       0   118.8    .045       0   136.8     .08       0
Bank Sta=118.8,136.8
XS Rating Curve= 0 ,0
Exp/Cntr=0.3,0.1

Type RM Length L Ch R = 1 ,211.6   ,74.2,73.2,77.1
XS GIS Cut Line= 6
     1643612.172      615852.732      1643563.76      615877.578
     1643573.656      616000.494     1643574.786      616062.763
     1643573.135      616098.411     1643588.588      616185.108
#Sta/Elev= 30
       0  712.01     9.1  706.14    18.1  700.02    45.4  680.26    54.4  674.08
    63.9  672.93      83     671    92.5   670.3   139.9  668.74   149.4  668.52
   177.7  668.29   186.7   667.8   195.7  667.04   204.7  665.71   213.7  663.25
   222.5  659.93     229  657.76   231.2  657.03     240  656.83     249659.7407
   259.6  664.28   269.4  666.97   280.9     668   290.1  668.36   299.4  668.96
   327.1  671.56   336.3  672.63   345.5  674.84   354.8   679.3     364   685.9
#Mann= 3 , 0 , 0
       0     .08       0     229    .045       0     249     .08       0
Bank Sta=229,249
XS Rating Curve= 0 ,0
Exp/Cntr=0.3,0.1

Type RM Length L Ch R = 1 ,138.4   ,98.7,84,63.5
XS GIS Cut Line= 6
     1643600.732      615831.449     1643506.255      615866.308
     1643513.463      615949.509     1643502.178      616078.849
     1643493.498      616097.946     1643539.107      616178.663
#Sta/Elev= 30
       0  711.93     9.2  705.72    18.3  698.93    45.8  675.84    54.9  670.05
    64.1  667.71    82.4  666.52    91.6   663.5   100.7  658.93   153.2  659.53
   168.9  659.18   224.1  659.48   240.1  658.97   263.9  659.58   271.7   659.2
   278.4  658.09   292.4654.9186   296.4  653.98   305.4  653.61   314.4655.5809
   319.9  656.85   324.9  658.83     336  661.91   345.3  665.78   354.6  667.24
   373.1  667.41   391.7  669.67   410.2   672.4   419.5  674.28   428.7     678
#Mann= 3 , 0 , 0
       0      .1       0   292.4    .045       0   314.4     .08       0
#XS Ineff= 2 , 0
       0     260     662               0
Permanent Ineff=
       F       F
Bank Sta=292.4,314.4
XS Rating Curve= 0 ,0
Exp/Cntr=0.3,0.1

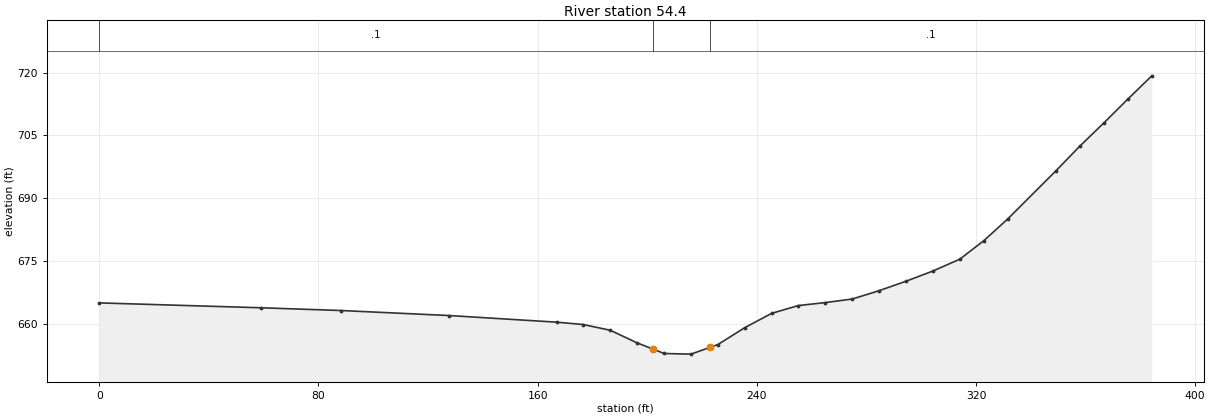
Type RM Length L Ch R = 1 ,54.4    ,49.9,54.4,58.5
XS GIS Cut Line= 3
     1643294.562      615939.994     1643495.343      616181.586
      1643529.55       616242.75
#Sta/Elev= 29
       0   665.1    58.9  663.94    88.4  663.28   127.6  662.09   166.9  660.51
   176.7  659.94   186.5  658.58   196.3  655.58     202654.1194   206.2  653.04
     216  652.89     223654.5195   225.8  655.17   235.6  659.19   245.4   662.6
   255.2  664.47     265  665.17   274.9  666.03   284.7  668.02   294.5  670.27
   304.3   672.7   314.1  675.51   322.9  679.94   331.6   685.1   349.2  696.58
   357.9  702.44   366.7     708   375.4  713.64   384.2  719.22
#Mann= 3 , 0 , 0
       0      .1       0     202    .045       0     223      .1       0
Bank Sta=202,223
XS Rating Curve= 0 ,0
Exp/Cntr=0.3,0.1

Chan Stop Cuts=-1
Use User Specified Reach Order=0
Composite Channel Slope=5